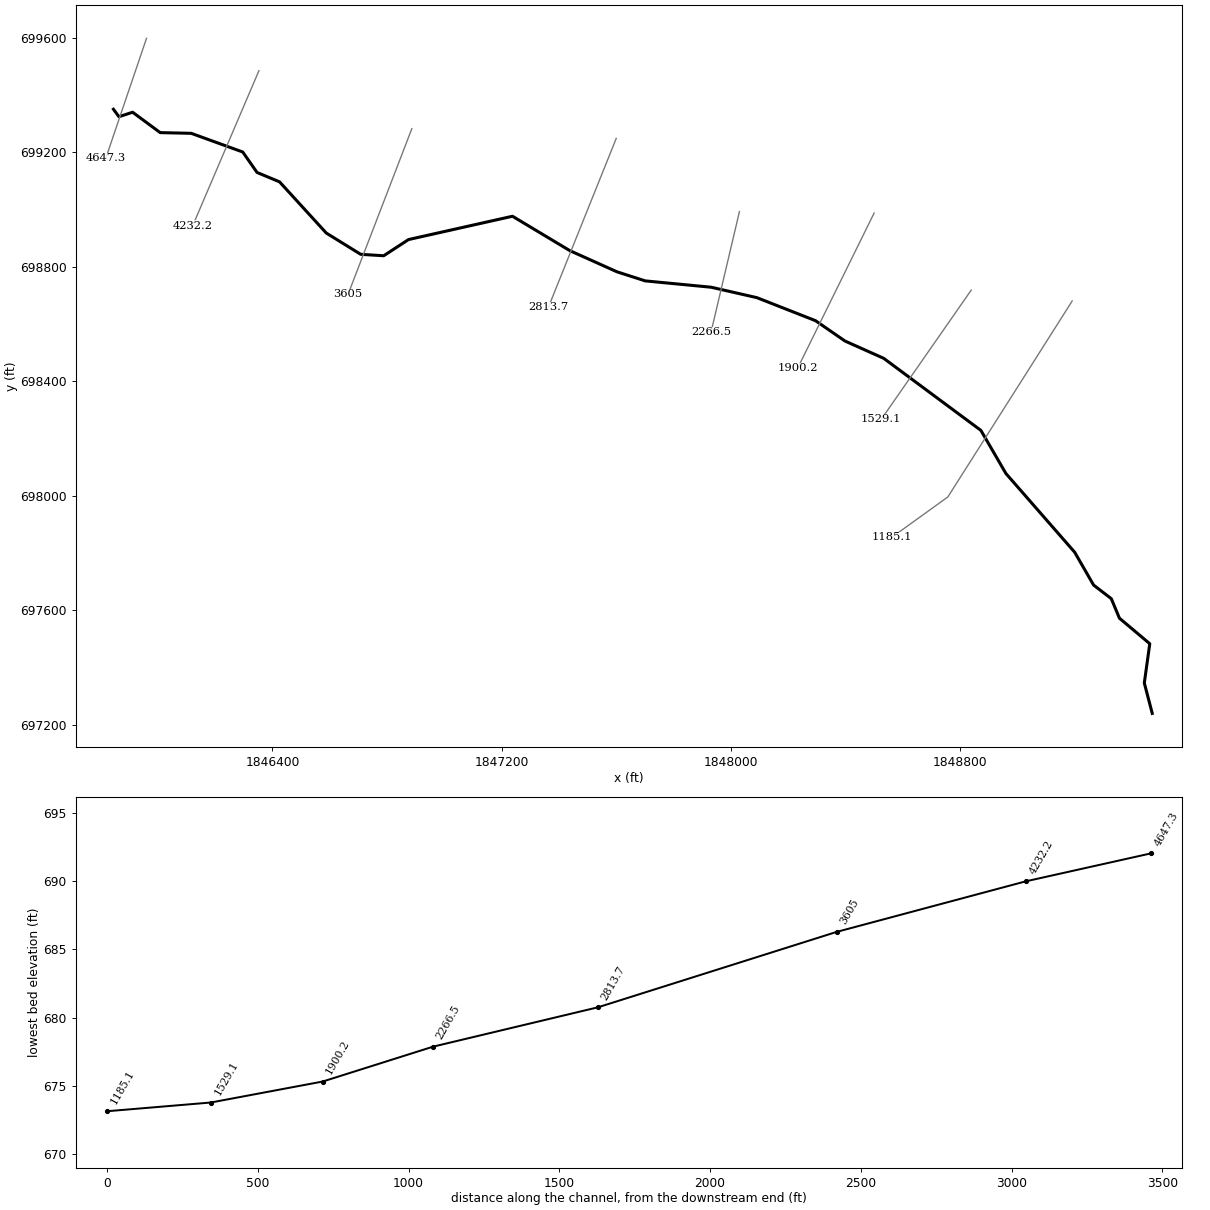
--- CainRun.prj (project) ---

Proj Title=CainRun
Current Plan=p01
Default Exp/Contr=0,0
English Units
Geom File=g01
Flow File=f01
Plan File=p01
BEGIN DESCRIPTION:
AMEC Environment & Infrastructure, 2013
Projection: NAD 1983 State Plane West Virginia South FIPS 4702 (US Feet)
Vertical Datum: NAVD 1988
END DESCRIPTION:
DSS Export Rating Curves= 0
DSS Export Rating Curve Sorted= 0
DSS Export Volume Flow Curves= 0
DXF OffsetX= 0
DXF OffsetY= 0
DXF ScaleX= 0
DXF ScaleY= 0

--- CainRun.p01 (plan) ---

Plan Title=Floodplain
Program Version=4.00
Geom File=g01
Flow File=f01
K Sum by GR=0
Std Step Tol=0.01
Critical Tol=0.01
Num of Std Step Trials=20
Max Error Tol=0.3
Flow Tol Ratio=0.001
Split Flow NTrial=30
Split Flow Tol=0.02
Split Flow Ratio=0.02
Log Output Level=0
Friction Slope Method=1
Unsteady Friction Slope Method=2
Unsteady Bridges Friction Slope Method=1
Global Log Level=0
CheckData=False
Run HTab=0
Run UNet=0
Run PostProcess=0
UNET Theta=0
UNET Theta Warmup=0
UNET ZTol=0
UNET ZSATol=0
UNET MxIter=0
UNET MaxInSteps=0
UNET DtIC=0
UNET DtMin=0
UNET MaxCRTS=0
UNET WFStab=0
UNET SFStab=0
UNET WFX=0
UNET SFX=0
UNET DSS MLevel=0
UNET DZMax Abort=0
UNET Convert EG Bridges=0
UNET Use Existing IB Tables=0
UNET Froude Limit=0
UNET Froude Power=0
Write IC File=0
Echo Input=False
Echo Output=False
Write Detailed=0

--- CainRun.f01 (steady flow) ---

Flow Title=NFF Regression Equation
Program Version=4.10
Number of Profiles= 1
Profile Names=P100yr
River Rch & RM=CainRun,Main            ,4647.3
885.6909
River Rch & RM=CainRun,Main            ,2266.5
 938.921
River Rch & RM=CainRun,Main            ,1185.1
1041.258
Boundary for River Rch & Prof#=CainRun,Main            , 1
Up Type= 0
Dn Type= 3
Dn Slope=0.0002
DSS Import GetInterval= 0
DSS Import GetPeak= 0
DSS Import FillOption= 0

--- CainRun.g01 (geometry) ---

Geom Title=USGS 3m DEM
Program Version=4.10

River Reach=CainRun         ,Main
Reach XY= 30
      1845844.57      699349.458     1845863.677      699323.408
     1845911.504      699339.042     1846007.834      699267.841
     1846116.228      699265.382     1846296.147      699200.128
     1846346.085      699128.692     1846424.677      699095.931
     1846587.948      698917.053     1846708.067        698842.8
     1846788.506      698837.773     1846875.229      698894.331
     1847238.304      698975.748     1847438.867      698855.455
      1847603.48      698781.619     1847701.981      698749.973
     1847932.238      698727.843     1848092.026      698691.383
      1848296.83      698610.923     1848399.756      698539.867
     1848534.733      698479.592     1848874.375      698227.761
     1848961.611      698077.375       1849201.9      697802.228
     1849267.906      697687.605     1849329.806      697640.007
     1849358.208      697571.866     1849464.178      697482.678
     1849445.084       697345.47     1849472.835      697239.403

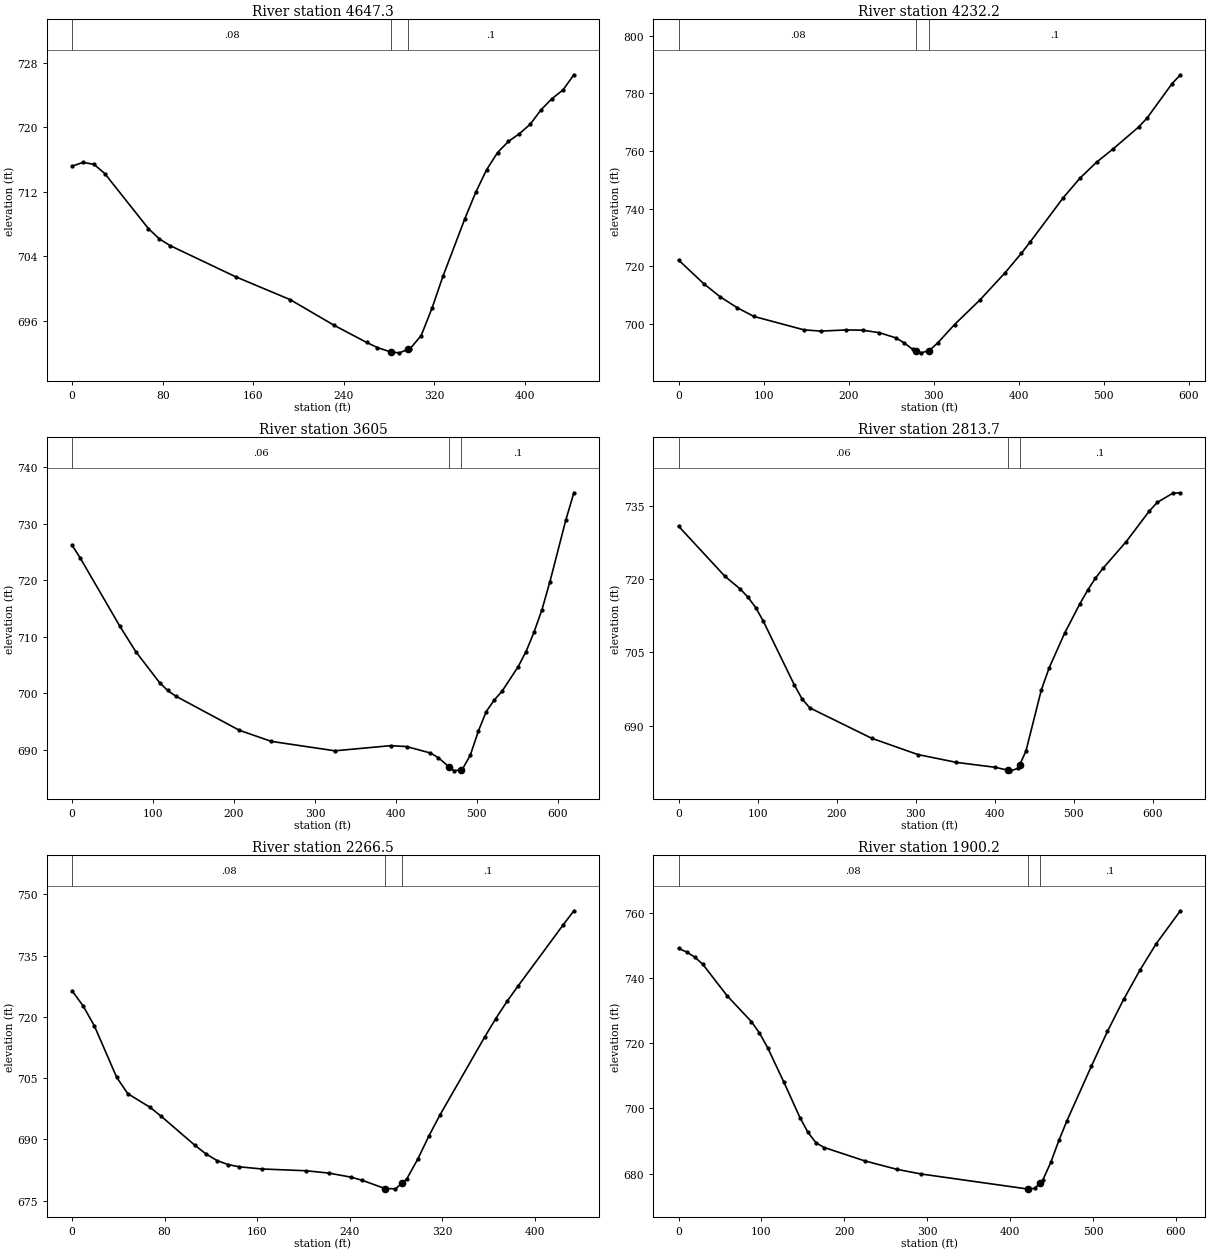
Type RM Length L Ch R = 1 ,4647.3  ,416.2,415,410.8
XS GIS Cut Line= 2
     1845960.042      699597.157     1845817.497      699177.591
#Sta/Elev= 30
       0   715.2     9.6  715.66    19.3  715.43    28.9  714.28    67.4  707.46
    77.1  706.18    86.7  705.34   144.5  701.48   192.7  698.64   231.2  695.48
   260.1  693.34   269.7   692.7   281.6  692.15     289  692.05   296.6  692.47
   298.6  692.58   308.3   694.2   317.9  697.61   327.5  701.54   346.8  708.66
   356.4  711.94     366  714.74   375.7  716.88   385.3  718.26     395  719.22
   404.6   720.4   414.2   722.2   423.8  723.57   433.5  724.65   443.1  726.53
#Mann= 3 , 0 , 0
       0     .08       0   281.6    .045       0   296.6      .1       0
Bank Sta=281.6,296.6
XS Rating Curve= 0 ,0
Exp/Cntr=0.3,0.1

Type RM Length L Ch R = 1 ,4232.2  ,626.3,627.2,627.7
XS GIS Cut Line= 2
     1846352.712      699484.197     1846121.014      698941.801
#Sta/Elev= 30
       0  722.22    29.5  714.02    49.2  709.39    68.8  705.69    88.5  702.64
   147.4  697.98   167.1  697.54   196.6  697.94   216.3  697.86   235.9     697
   255.6  695.18   265.4  693.42   275.2   691.2   279.7  690.65   285.1     690
   294.7   690.8   304.7  693.46   324.4  699.82   353.9  708.24   383.4  717.65
     403  724.56   412.9  728.32   452.2  743.83   471.8  750.61   491.5  756.19
   511.2  760.87   540.7  768.34   550.5   771.4     580  783.38   589.8  786.49
#Mann= 3 , 0 , 0
       0     .08       0   279.7    .045       0   294.7      .1       0
Bank Sta=279.7,294.7
XS Rating Curve= 0 ,0
Exp/Cntr=0.3,0.1

Type RM Length L Ch R = 1 ,3605    ,791.7,791.3,790.6
XS GIS Cut Line= 2
     1846886.841      699281.734     1846664.126      698703.457
#Sta/Elev= 30
       0  726.16     9.8  723.97      59  711.85    78.7  707.35   108.2  701.86
     118   700.5   127.9   699.5   206.6  693.46   245.9   691.5   324.6  689.83
   393.4  690.74   413.1  690.58   442.6  689.44   452.5   688.6   465.4  687.01
   472.1  686.29   480.4  686.52     482  686.57   491.8  689.05   501.6  693.25
   511.5  696.77   521.3  698.78   531.2   700.4   550.8  704.67   560.7  707.38
   570.5   710.8   580.3  714.76   590.2  719.75   609.8  730.63   619.7  735.43
#Mann= 3 , 0 , 0
       0     .06       0   465.4    .045       0   480.4      .1       0
Bank Sta=465.4,480.4
XS Rating Curve= 0 ,0
Exp/Cntr=0.3,0.1

Type RM Length L Ch R = 1 ,2813.7  ,543.6,547.2,550.4
XS GIS Cut Line= 2
     1847600.652      699247.519     1847363.974      698658.513
#Sta/Elev= 30
       0  730.87    58.6  720.62    78.1  717.99    87.9  716.31    97.7  714.18
   107.4  711.36   146.5  698.35   156.2  695.51     166  693.66   244.2  687.44
   302.7   684.1   351.6  682.49   400.4  681.49   416.8  680.89   419.9  680.76
   429.7  681.29   431.8  682.05   439.5  684.82     459  697.35   468.8  701.82
   488.3  708.91   507.8     715   517.6  717.76   527.4  720.22   537.1  722.26
   566.4  727.72   595.7  733.99   605.5  735.72     625   737.6   634.8  737.71
#Mann= 3 , 0 , 0
       0     .06       0   416.8    .045       0   431.8      .1       0
Bank Sta=416.8,431.8
XS Rating Curve= 0 ,0
Exp/Cntr=0.3,0.1

Type RM Length L Ch R = 1 ,2266.5  ,371.5,366.3,361.2
XS GIS Cut Line= 2
     1848030.976      698992.014     1847931.463      698569.759
#Sta/Elev= 30
       0   726.4     9.6  722.68    19.3  717.78    38.6  705.18    48.2  701.18
    67.5  697.83    77.1  695.64     106  688.58   115.7  686.44   125.3   684.8
     135  683.81   144.6  683.27   163.9  682.74   202.4   682.3   221.7  681.74
     241  680.74   250.6  679.99   270.4  677.95   279.6  677.87   285.4   679.3
   289.2  680.23   298.9  685.17   308.5  690.84   318.1     696   356.7  715.07
   366.3  719.59     376  723.79   385.6  727.58   424.2  742.41   433.8     746
#Mann= 3 , 0 , 0
       0     .08       0   270.4    .045       0   285.4      .1       0
Bank Sta=270.4,285.4
XS Rating Curve= 0 ,0
Exp/Cntr=0.3,0.1

Type RM Length L Ch R = 1 ,1900.2  ,374.2,371.2,367.5
XS GIS Cut Line= 2
     1848501.461      698987.049     1848233.895      698444.258
#Sta/Elev= 30
       0  749.11     9.8  748.02    19.5  746.47    29.3  744.24    58.6  734.58
    87.8  726.67    97.6  723.15   107.4  718.68   126.9  708.14   146.4  697.21
   156.2  692.61   165.9  689.41   175.7     688   224.5   683.9   263.5  681.29
   292.8  679.86   419.7  675.31   421.1  675.33   429.5  675.43   436.1  677.12
   439.2  677.92     449  683.46   458.8   690.2   468.5  696.25   497.8   712.9
   517.3  723.65   536.8  733.46   556.4  742.42   575.9  750.49   605.2  760.68
#Mann= 3 , 0 , 0
       0     .08       0   421.1    .045       0   436.1      .1       0
Bank Sta=421.1,436.1
XS Rating Curve= 0 ,0
Exp/Cntr=0.3,0.1

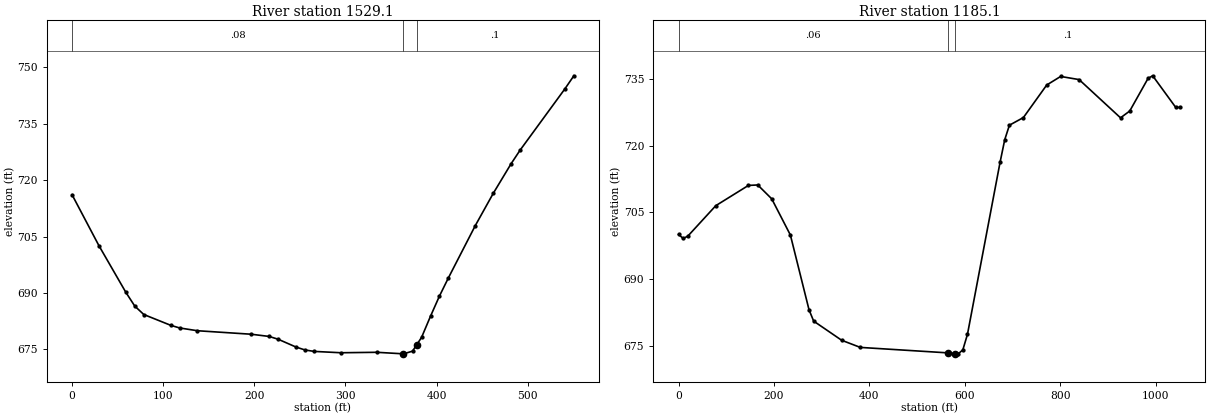
Type RM Length L Ch R = 1 ,1529.1  ,340.8,344,346
XS GIS Cut Line= 2
     1848840.523      698717.683     1848525.848      698265.842
#Sta/Elev= 30
       0  716.12    29.5  702.55      59  690.15    68.8  686.48    78.7  684.24
   108.2  681.37     118  680.66   137.6  679.92   196.6  678.99   216.3   678.4
   226.2  677.65   245.8  675.57   255.6   674.8   265.5  674.42     295  674.06
   334.3  674.18     363  673.78   363.8  673.77   373.6  674.49     378  676.12
   383.5  678.15   393.3  683.78   403.1  689.14     413  694.02   442.5  707.93
   462.1  716.47   481.8   724.4   491.6  727.99   540.8  744.32   550.6  747.79
#Mann= 3 , 0 , 0
       0     .08       0     363    .045       0     378      .1       0
Bank Sta=363,378
XS Rating Curve= 0 ,0
Exp/Cntr=0.3,0.1

Type RM Length L Ch R = 1 ,1185.1  ,1204.3,1185.1,1165
XS GIS Cut Line= 3
     1849193.273      698679.849     1848758.971      697995.389
     1848563.469      697854.549
#Sta/Elev= 30
       0  700.02     9.8  699.11    19.5  699.64    78.1   706.5   146.5  711.06
     166  711.16   195.3  708.04   234.4  699.89   273.5  683.04   283.2   680.5
   341.8  676.19   380.9  674.58   564.1  673.35   579.1  673.19     586  673.13
   595.8  674.02   605.5  677.52   673.9  716.31   683.6  721.35   693.4  724.62
   722.7  726.34   771.6  733.67   800.8   735.6   839.5  734.89   926.3  726.28
   945.6  727.82   984.1  735.19   993.7  735.75  1041.9  728.64  1051.6  728.61
#Mann= 3 , 0 , 0
       0     .06       0   564.1    .045       0   579.1      .1       0
Bank Sta=564.1,579.1
XS Rating Curve= 0 ,0
Exp/Cntr=0.3,0.1

Chan Stop Cuts=-1
Use User Specified Reach Order=0
Composite Channel Slope=5